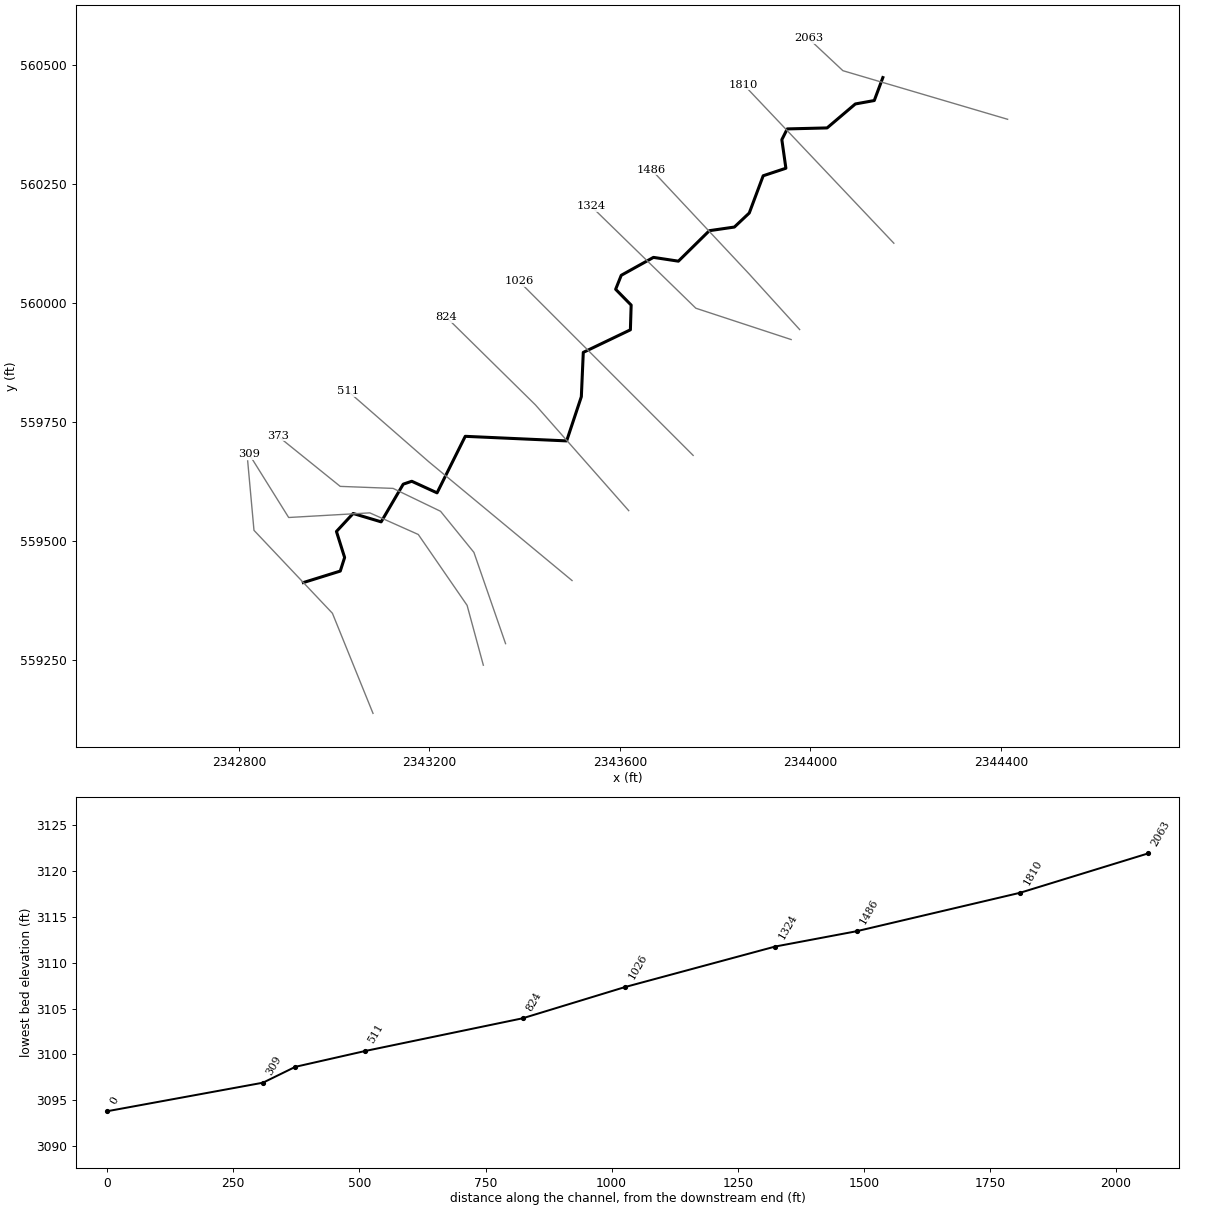
--- BIGRN.prj (project) ---

Proj Title=BIGRN
Current Plan=p01
Default Exp/Contr=0,0
English Units
Geom File=g01
Flow File=f01
Plan File=p01
Background Map Layer=Inundation Boundary (01pct Value_0)
BEGIN DESCRIPTION:
----------MODEL BY WOOD PLC 2021----------
Stream Name: Big Run I
Flood Zone: Enhanced Approximate
Pocahontas County, WV
HEC-RAS Version: RAS 6.1
Vertical Datum: NAVD88
Projection: NAD 1983 StatePlane West Virginia S FIPS 4702 (US Feet)
Terrain: 1-meter LIDAR (FEMA Region III 3DEP collected 2016-2018)
Land Use: 2019 NLCD
Hydrologic Method:
WV SIR2010-5033 regression equations
Model Notes:
coincident peak / KWSEL tie in with BFLFK at XS 13136
END DESCRIPTION:
DSS Export Rating Curves= 0
DSS Export Rating Curve Sorted= 0
DSS Export Volume Flow Curves= 0
DXF OffsetX= 0
DXF OffsetY= 0
DXF ScaleX= 0
DXF ScaleY= 0

--- BIGRN.p01 (plan) ---

Plan Title=Floodplain
Program Version=6.10
Short Identifier=Floodplain
Geom File=g01
Flow File=f01
Subcritical Flow
K Sum by GR= 0
Std Step Tol= 0.01
Critical Tol= 0.01
Num of Std Step Trials= 20
Max Error Tol= 0.3
Flow Tol Ratio= 0.001
Split Flow NTrial= 30
Split Flow Tol= 0.02
Split Flow Ratio= 0.02
Log Output Level= 0
Friction Slope Method= 1
Unsteady Friction Slope Method= 2
Unsteady Bridges Friction Slope Method= 1
Parabolic Critical Depth
Global Vel Dist= 0 , 0 , 0
Global Log Level= 0
CheckData=True
Encroach Param=-1 ,0,0, 0
Mapping Interval=1HOUR
Computation Time Step Use Courant=        0
Computation Time Step Use Time Series=    0
Computation Time Step Count To Double=0
Computation Time Step Max Doubling=0
Computation Time Step Max Halving=0
Computation Time Step Residence Courant=0
Run HTab= 0
Run UNet= 0
Run Sediment= 0
Run PostProcess= 0
Run WQNet= 0
Run RASMapper=-1
UNET Theta= 0
UNET Theta Warmup= 0
UNET ZTol= 0
UNET ZSATol= 0
UNET MxIter= 0
UNET Max Iter WO Improvement= 0
UNET MaxInSteps= 0
UNET DtIC= 0
UNET DtMin= 0
UNET MaxCRTS= 0
UNET WFStab= 0
UNET SFStab= 0
UNET WFX= 1
UNET SFX= 1
UNET Gravity=32.174
UNET 1D Methodology=Finite Difference
UNET DSS MLevel= 1
UNET Pardiso=0
UNET DZMax Abort= 0
UNET Use Existing IB Tables= 0
UNET Froude Reduction=False
UNET Froude Limit= 0
UNET Froude Power= 0
UNET D1 Cores= 0
UNET WindReference=Eulerian
UNET WindDragFormulation=Hsu (1988)
UNET D2 Coriolis=0
UNET D2 Cores= 0
UNET D2 Theta= 1
UNET D2 Theta Warmup= 1
UNET D2 Z Tol= 0.01
UNET D2 Volume Tol= 0.01
UNET D2 Max Iterations= 20
UNET D2 Equation= 0
UNET D2 RampUpFraction=0.1
UNET D2 TimeSlices= 1
UNET D2 Turbulence Formulation=Non-Conservative (original)
UNET D2 Eddy Viscosity=0.3
UNET D2 Transverse Eddy Viscosity=0.1
UNET D2 Smagorinsky Mixing=0
UNET D2 BCVolumeCheck=0
UNET D2 Cores=0
UNET D2 SolverType=PARDISO (Direct)
UNET D2 Minimum Iterations= 2147483647
UNET D2 Maximum Iterations= 2147483647
UNET D2 Restart Number= 10
UNET D2 Relaxation Coeff=1.3
UNET D2 SOR Precondition Iterations= 10
UNET D2 ILUT Maximum Fill= 8
UNET D2 ILUT Tolerance=1E-08
UNET D1D2 MaxIter= 0
UNET D1D2 ZTol=0.01
UNET D1D2 QTol=0.1
UNET D1D2 MinQTol=1
Write IC File= 0
Write IC File at Fixed DateTime=0
Write IC File at Sim End=0
Echo Input=False
Echo Parameters=False
Echo Output=False
Write Detailed= 0
HDF Write Warmup=0
HDF Write Time Slices=0
HDF Flush=0
HDF Compression= 1
HDF Chunk Size= 1
HDF Spatial Parts= 1
HDF Use Max Rows=0
HDF Fixed Rows= 1
Calibration Method= 0
Calibration Iterations= 20
Calibration Max Change=0.05
Calibration Tolerance=0.2
Calibration Maximum=1.5
Calibration Minimum=0.5
Calibration Optimization Method= 1
WQ AD Non Conservative
WQ ULTIMATE=-1
WQ Max Comp Step=1HOUR
WQ Output Interval=15MIN
WQ Output Selected Increments= 0
WQ Output face flow=0
WQ Output face velocity=0
WQ Output face area=0
WQ Output face dispersion=0
WQ Output cell volume=0
WQ Output cell surface area=0
WQ Output cell continuity=0
WQ Output cumulative cell continuity=0
WQ Output face conc=0
WQ Output face dconc_dx=0
WQ Output face courant=0
WQ Output face peclet=0
WQ Output face adv mass=0
WQ Output face disp mass=0
WQ Output cell mass=0
WQ Output cell source sink temp=0
WQ Output nsm pathways=0
WQ Output nsm derived pathways=0
WQ Create Restart=0
WQ Fixed Restart=0
WQ System Summary=0
WQ Write To DSS=0
Sorting and Armoring Iterations= 10
XS Update Threshold= 0.02
Bed Roughness Predictor= 0
Hydraulics Update Threshold= 0.02
Energy Slope Method= 1
Volume Change Method= 1
Sediment Retention Method= 0
Sediment TS Multiplier= 1
Warm Up Method= 0
XS Weighting Method= 0
Number of US Weighted Cross Sections= 1
Number of DS Weighted Cross Sections= 1
Upstream XS Weight=0
Main XS Weight=1
Downstream XS Weight=0
Number of DS XS's Weighted with US Boundary= 1
Upstream Boundary Weight= 1
Weight of XSs Associated with US Boundary= 0
Number of US XS's Weighted with DS Boundary= 1
Downstream Boundary Weight= 0.5
Weight of XSs Associated with DS Boundary= 0.5
Percentile Method= 0
Sediment Output Level= 3
Mass or Volume Output= 0
Output Increment Type= 1
Profile and TS Output Increment= 1
Transport Output Increment 1
XS Output Flag= 0
XS Output Increment= 10
Read HDF5 Sediment Hotstart= 0
Sediment Hotstart Type= 0
Write Gradation File= 0
Read Gradation Hotstart= 0
Write HDF5 File= 1
Write Binary Output= 1
Write DSS Sediment File= 0
DSS Sediment Output Type= 1
SV Curve= 0
Specific Gage Flag= 0
Subcell Erosion Methods= 0
Subcell Deposition Methods= 0
Advection Scheme= 1
Matrix Solver= 0
Implicit Weighting Factor= 1
Maximum Outer Loop Convergence Iterations= 5
Convergence Maximum Absolute= 0.001
Convergence RMSE= 0.0001
Grain Fractions Max Abs Error= 0.001
Max Subgrid Regions= 1
Max Subgrid Length Scale= 3.402823E+38
Initial Layer Thickness= 3.402823E+38
Min Layer Thickness= 3.402823E+38
Max Layer Thickness= 3.402823E+38
Number of Layers= 5

--- BIGRN.f01 (steady flow) ---

Flow Title=Flow
Program Version=6.10
Number of Profiles= 6
Profile Names=01pct,10pct,04pct,02pct,0_2pct,01plus
River Rch & RM=BIGRN,Main            ,2063
     568     300     399     481     794     841
River Rch & RM=BIGRN,Main            ,0
    1010     546     718     859    1400    1490
Boundary for River Rch & Prof#=BIGRN,Main            , 1
Up Type= 0
Dn Type= 1
Dn Known WS=3097.9
Boundary for River Rch & Prof#=BIGRN,Main            , 2
Up Type= 0
Dn Type= 1
Dn Known WS=3096.9
Boundary for River Rch & Prof#=BIGRN,Main            , 3
Up Type= 0
Dn Type= 1
Dn Known WS=3097.3
Boundary for River Rch & Prof#=BIGRN,Main            , 4
Up Type= 0
Dn Type= 1
Dn Known WS=3097.5
Boundary for River Rch & Prof#=BIGRN,Main            , 5
Up Type= 0
Dn Type= 1
Dn Known WS=3098.3
Boundary for River Rch & Prof#=BIGRN,Main            , 6
Up Type= 0
Dn Type= 1
Dn Known WS=3098.4
DSS Import GetInterval= 0
DSS Import GetPeak= 0
DSS Import FillOption= 0

--- BIGRN.g01 (geometry) ---

Geom Title=Geometry
Program Version=6.10

River Reach=BIGRN           ,Main
Reach XY= 30
2344152.32505697560473.8400721552344134.27850512560425.604276225
2344094.54761352560418.4130176452344035.22128855 560368.07551989
2343951.53707272560366.007938728 2343940.1778435560343.380031243
2343948.67913882560283.4080383032343901.01092705560267.597046331
2343871.74786225560189.3422815652343840.52056247560159.894833893
2343787.91896163560152.2609909032343722.92893419560088.234872237
2343670.55994441560096.1908930692343602.90489596560058.563999817
2343591.15032634560029.1762633172343623.70997249559996.017208889
2343622.11187857559944.0816172212343523.17900555559896.671935141
2343519.09305574559803.6189716612343488.23747438559710.792713732
 2343275.2851444559720.3904635612343216.08578773559601.653168246
2343162.97532962559626.0097468052343145.04623167559619.920520157
2343098.70150806 559540.762541982343039.84040532559558.353057995
2343004.78043608559520.5703251512343021.95100538 559465.92607747
2343012.81814964559437.4028405552342935.31315118559413.272979975

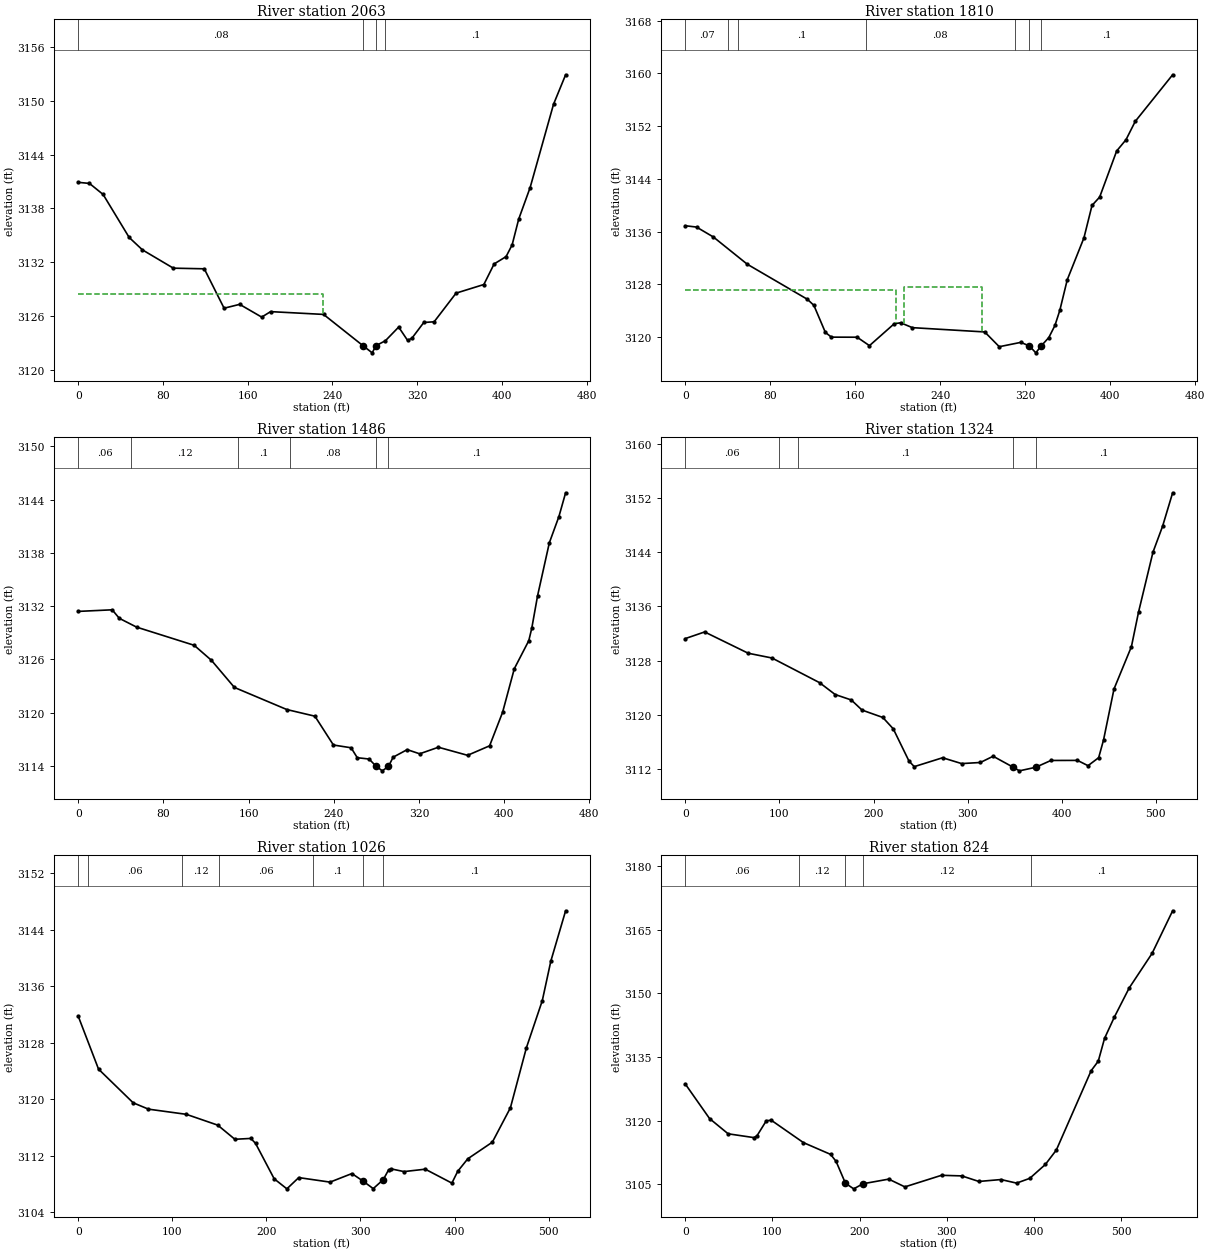
Type RM Length L Ch R = 1 ,2063    ,253.8,253.8,253.8
XS GIS Cut Line= 3
2344414.34089636560386.2093456612344068.44821713560488.255017577
2343995.88484769560556.224418515
#Sta/Elev= 30
       0  3140.9    10.6 3140.78    23.5 3139.55    48.1 3134.76    60.6 3133.38
    89.8 3131.34     119 3131.27   137.7 3126.88   152.4 3127.31   173.2 3125.89
   181.6  3126.5   231.6 3126.19   269.2 3122.67   277.5 3121.91   281.1 3122.71
     290 3123.26   302.5 3124.78   310.9  3123.3     315 3123.54   326.2 3125.29
     336 3125.37   356.7 3128.56   382.9 3129.52   392.6 3131.81   403.9 3132.63
   409.6 3133.93   415.8  3136.8   426.6 3140.32   448.7  3149.6   460.1 3152.88
#Mann= 4 ,-1,0
       0     .08       0   269.2    .045       0   281.1     .08       0
     290      .1       0
#XS Ineff= 2 , 0
          231.27 3128.49
Permanent Ineff=
       F       F
Bank Sta=269.2,281.1
XS Rating Curve= 0 ,0
Exp/Cntr=0.3,0.1

Type RM Length L Ch R = 1 ,1810    ,322.8,324,319.8
XS GIS Cut Line= 2
2344175.42921242560125.9178148622343859.98906301560459.039587006
#Sta/Elev= 30
       0  3136.9    10.6  3136.7    26.5 3135.19    58.4 3131.06     115 3125.74
   121.1 3124.82   131.9 3120.72   137.6    3120   161.8 3119.99   173.4 3118.71
   196.7 3122.03   202.8 3122.18   213.8 3121.44   281.9 3120.79   295.6 3118.55
   315.9 3119.21     324 3118.66     330 3117.62     335 3118.66   342.2 3119.93
     348 3121.77   352.6 3124.07   359.6 3128.71   375.3 3135.06   382.9 3139.98
   390.1 3141.25   406.1 3148.24   414.9 3149.95   423.6 3152.73   458.8  3159.8
#Mann= 7 ,-1,0
       0     .07       0      40     .06       0      50      .1       0
     170     .08       0     310      .1       0     324    .045       0
     335      .1       0
#XS Ineff= 2 ,-1
       0   198.5  3127.2  205.98  279.07 3127.68
Permanent Ineff=
       F       F
Bank Sta=324,335
XS Rating Curve= 0 ,0
Exp/Cntr(USF)=0,0
Exp/Cntr=0.3,0.1

Type RM Length L Ch R = 1 ,1486    ,158.3,161.4,162.8
XS GIS Cut Line= 3
2343977.60211568559944.5927740042343871.01523972560061.904377378
2343666.45595395560280.352572593
#Sta/Elev= 30
       0  3131.4    31.9 3131.58    38.6 3130.62    54.8 3129.63   108.9 3127.58
   125.1 3125.89   146.7 3122.83   195.9 3120.34   222.3 3119.59   239.7 3116.34
   256.3 3116.03   262.1 3114.91   273.2 3114.76   279.7 3113.96   285.6 3113.43
   291.4 3113.93   295.8 3114.97     309 3115.82   320.7 3115.35   338.3 3116.09
   365.7 3115.18   386.4 3116.25   398.6 3120.03   409.6 3124.94   423.2  3128.1
     426  3129.5   431.5 3133.19   442.5 3139.13   451.5 3142.09   457.8 3144.77
#Mann= 6 ,-1,0
       0     .06       0      50     .12       0     150      .1       0
   198.5     .08       0   279.7    .045       0   291.4      .1       0
Bank Sta=279.7,291.4
XS Rating Curve= 0 ,0
Exp/Cntr=0.3,0.1

Type RM Length L Ch R = 1 ,1324    ,297.6,298,296.6
XS GIS Cut Line= 3
2343959.71341518559923.6400508852343759.55744593559989.415687423
2343539.59805922560203.716954853
#Sta/Elev= 30
       0 3131.26    20.6 3132.24    66.9  3129.1    92.1  3128.4   142.7 3124.76
   159.3 3123.01   176.4 3122.21   187.8 3120.72   209.9 3119.63     221 3117.95
   237.7  3113.2   243.3 3112.38   273.4 3113.69   293.6 3112.83   313.5 3112.99
   327.1 3113.91   348.7 3112.27     355 3111.76   372.33112.283   388.5 3113.29
   416.7  3113.3   427.9 3112.52   439.2  3113.7   444.4 3116.32   455.5 3123.83
     474 3130.07   481.6 3135.19   496.9    3144   507.1 3147.82   517.8 3152.76
#Mann= 5 ,-1,0
       0     .06       0     100     .12       0     120      .1       0
   348.7    .045       0   372.3      .1       0
Bank Sta=348.7,372.3
XS Rating Curve= 0 ,0
Exp/Cntr(USF)=0,0
Exp/Cntr=0.3,0.1

Type RM Length L Ch R = 1 ,1026    ,201.5,202.7,201.4
XS GIS Cut Line= 2
2343753.89932665559680.3409221862343387.53610379560046.704145053
#Sta/Elev= 30
       0 3131.76    21.6 3124.27    58.4 3119.51    74.7 3118.61   114.9 3117.88
   148.3 3116.35   166.5 3114.35   183.5 3114.47   188.5 3113.77   208.3 3108.76
   221.8 3107.34   234.4 3108.93   267.7 3108.29   290.9  3109.5   302.3 3108.48
   313.6 3107.37   324.3 3108.65   329.9 3110.02   332.7 3110.16   346.3 3109.78
   368.9 3110.12   397.2 3108.15   403.4 3109.82   414.1 3111.59   440.2 3113.94
   459.4  3118.8   476.4 3127.29   493.3 3133.96   502.4 3139.56   518.1 3146.67
#Mann= 7 ,-1,0
       0      .1       0      10     .06       0     110     .12       0
     150     .06       0     250      .1       0   302.3    .045       0
   324.3      .1       0
Bank Sta=302.3,324.3
XS Rating Curve= 0 ,0
Exp/Cntr(USF)=0,0
Exp/Cntr=0.3,0.1

Type RM Length L Ch R = 1 ,824     ,314.4,312.5,311.6
XS GIS Cut Line= 3
 2343618.5934374559564.285444895 2343422.6160552559786.457823719
2343235.37033855 559970.79298519
#Sta/Elev= 30
       0 3128.66    27.9  3120.5    49.2 3116.91    78.9 3116.01    82.3 3116.45
      93 3119.99    98.7  3120.1   135.5 3114.84   166.7 3112.06     173 3110.41
   183.7 3105.27   193.2 3103.94   203.9 3105.14   233.4 3106.23   251.9  3104.4
   293.9 3107.13   317.2 3106.99   336.7 3105.68   362.1 3106.13     380 3105.29
   395.1 3106.41     413 3109.68   425.6 3113.08   465.5 3131.77   473.7 3134.03
   480.9  3139.4   492.2 3144.44   509.2 3151.29   535.4 3159.42     559 3169.47
#Mann= 5 ,-1,0
       0     .06       0     130     .12       0   183.7    .045       0
   203.9     .12       0  396.26      .1       0
Bank Sta=183.7,203.9
XS Rating Curve= 0 ,0
Exp/Cntr(USF)=0,0
Exp/Cntr=0.3,0.1

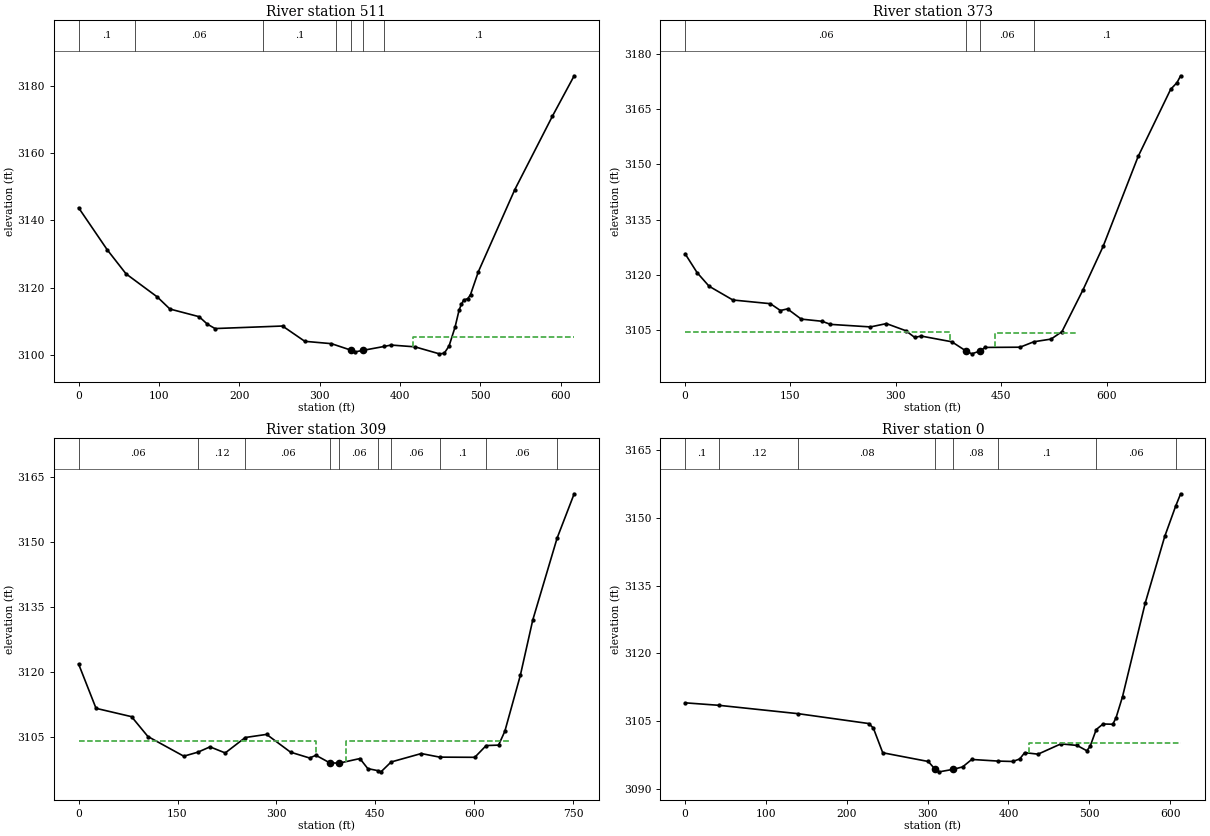
Type RM Length L Ch R = 1 ,511     ,123.6,138,143.7
BEGIN DESCRIPTION:
xs 4
END DESCRIPTION:
XS GIS Cut Line= 3
2343499.59441863559417.4935347052343198.50330625559667.125061294
2343028.54822775 559815.55755442
#Sta/Elev= 30
       0 3143.74    35.6 3131.27      59 3124.13      98 3117.25   113.6 3113.68
     150  3111.4   160.3 3109.17   169.8 3107.88   253.8 3108.63   281.5 3104.09
   314.7 3103.39   339.1 3101.45   344.2 3100.95   354.5 3101.43     380 3102.55
   388.9 3102.98   418.6 3102.45     449 3100.37     455 3100.52   461.1 3102.71
   468.6 3108.37   473.6  3113.4   476.4 3115.07   479.3 3116.33   484.5 3116.78
   487.8 3117.98   497.6  3124.8   542.9 3149.14   589.8 3170.99   616.8 3182.95
#Mann= 7 ,-1,0
       0      .1       0      70     .06       0     230      .1       0
     320     .06       0   339.1    .045       0   354.5     .06       0
     380      .1       0
#XS Ineff= 2 , 0
                          416.38         3105.33
Permanent Ineff=
       F       F
Bank Sta=339.1,354.5
XS Rating Curve= 0 ,0
Exp/Cntr(USF)=0,0
Exp/Cntr=0.5,0.3

Type RM Length L Ch R = 1 ,373     ,64.3,64.3,64.3
BEGIN DESCRIPTION:
xs 3
END DESCRIPTION:
XS GIS Cut Line= 6
2343359.95277234 559284.979838052343293.46987089559476.648628391
 2343223.4506449 559562.934947292343123.72629273559611.028961103
2343012.68570201559615.2725505572342881.13442894559721.362286909
#Sta/Elev= 30
       0 3125.79    17.1 3120.67    34.1 3116.99      68 3113.25   121.4 3112.25
   135.7  3110.4   145.8 3110.84   165.3 3108.07     195 3107.48     207 3106.64
   263.9 3105.95   286.6 3106.85     314 3104.94   326.9 3103.11   336.1 3103.47
   379.7 3101.92   399.73099.453   408.2 3098.65   420.2 3099.45     427 3100.39
   476.9 3100.45   496.4 3101.92     521 3102.65   536.5 3104.66   566.6 3116.04
   595.1 3127.77     645 3152.17   691.3 3170.38   700.3 3172.19   705.5 3174.05
#Mann= 4 ,-1,0
       0     .06       0   399.7    .045       0   420.2     .06       0
   496.4      .1       0
#XS Ineff= 2 ,-1
       0   377.7  3104.5  440.96  557.893104.259
Permanent Ineff=
       F       F
Bank Sta=399.7,420.2
XS Rating Curve= 0 ,0
Exp/Cntr(USF)=0,0
Exp/Cntr=0.5,0.3

Type RM Length L Ch R = 1 ,309     ,308.8,308.8,308.8
BEGIN DESCRIPTION:
xs 2
END DESCRIPTION:
XS GIS Cut Line= 6
2343313.27328834559239.7148838732343279.19726503559365.381712905
2343176.66507117559514.232685656 2343074.8864081559559.641201224
2342904.44003982559549.8973190952342821.72417658559682.462716913
#Sta/Elev= 30
       0 3121.84    26.4 3111.61    80.3 3109.68   105.1 3105.09   159.5 3100.54
   181.2 3101.48   199.3  3102.7   222.4 3101.29   252.8 3104.86   285.2 3105.58
   321.5 3101.47   350.4 3100.12     360 3100.75     381    3099   395.2 3098.93
   426.7 3099.99   438.7 3097.67   454.1 3097.19   458.7 3096.92   474.1  3099.2
   519.8 3101.15   547.8 3100.32     601 3100.28   618.3    3103   637.1  3103.1
   646.6  3106.3   670.1 3119.22     689 3132.05   725.9 3150.97   751.8 3161.23
#Mann= 10 ,-1,0
       0     .06       0   181.2     .12       0   252.8     .06       0
     381    .045       0   395.2     .06       0   454.1      .1       0
   474.1     .06       0   547.8      .1       0   618.3     .06       0
   725.9      .1       0
#XS Ineff= 2 ,-1
       0   359.5    3104   405.8  655.49    3104
Permanent Ineff=
       F       F
Bank Sta=381,395.2
XS Rating Curve= 0 ,0
Exp/Cntr(USF)=0,0
Exp/Cntr=0.5,0.3

Type RM Length L Ch R = 1 ,0       ,305.9,297.6,282.9
XS GIS Cut Line= 4
2343081.56004884559138.5378096162342996.34597676559348.732520747
2342831.59877073   559522.9479572342818.34324841559668.758702559
#Sta/Elev= 30
       0 3109.08    41.7 3108.53   140.2 3106.67   227.4 3104.49   232.9 3103.48
   244.5 3098.03   300.8  3096.1   308.6 3094.52   314.4 3093.81     332 3094.38
   343.3  3094.9   354.6 3096.55   387.1 3096.19   405.5  3096.1     414 3096.67
   420.1 3098.06   436.6 3097.72   464.9    3100   484.9 3099.65   496.9 3098.48
     501 3099.44   508.6 3103.17     517  3104.4   529.1 3104.34   533.1 3105.78
   541.1 3110.44   569.2 3131.16   593.3 3145.88   606.7 3152.53     613 3155.33
#Mann= 8 ,-1,0
       0      .1       0    41.7     .12       0   140.2     .08       0
   308.6    .045       0     332     .08       0   387.1      .1       0
   508.6     .06       0   606.7      .1       0
#XS Ineff= 2 , 0
                          424.82         3100.09
Permanent Ineff=
       F       F
Bank Sta=308.6,332
XS Rating Curve= 0 ,0
Exp/Cntr(USF)=0,0
Exp/Cntr=0.3,0.1
LCMann Table=0

Chan Stop Cuts=-1
Use User Specified Reach Order=0
Composite Channel Slope=5